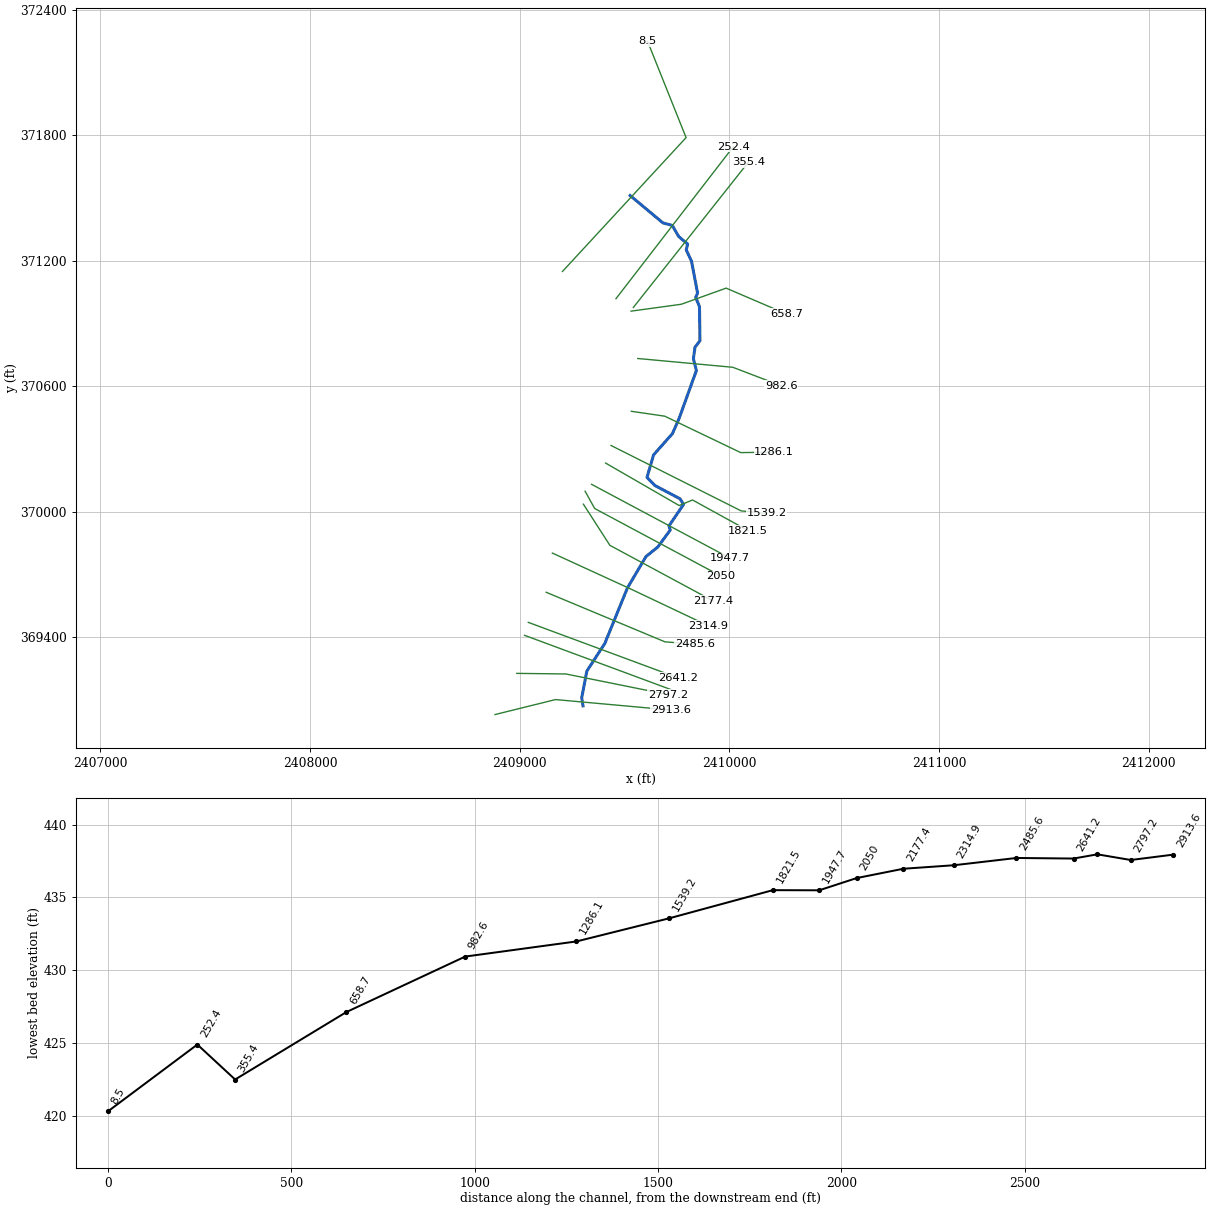
--- HOKERUNTRB.prj (project) ---

Proj Title=HOKERUNTRB
Current Plan=p01
Default Exp/Contr=0,0
English Units
Geom File=g01
Flow File=f01
Plan File=p01
BEGIN DESCRIPTION:
END DESCRIPTION:
DSS Export Rating Curves= 0
DSS Export Rating Curve Sorted= 0
DSS Export Volume Flow Curves= 0
DXF OffsetX= 0
DXF OffsetY= 0
DXF ScaleX= 0
DXF ScaleY= 0

--- HOKERUNTRB.p01 (plan) ---

Plan Title=Floodplain
Program Version=4.00
Geom File=g01
Flow File=f01
K Sum by GR=0
Std Step Tol=0.01
Critical Tol=0.01
Num of Std Step Trials=20
Max Error Tol=0.3
Flow Tol Ratio=0.001
Split Flow NTrial=30
Split Flow Tol=0.02
Split Flow Ratio=0.02
Log Output Level=0
Friction Slope Method=1
Unsteady Friction Slope Method=2
Unsteady Bridges Friction Slope Method=1
Global Log Level=0
CheckData=False
Run HTab=0
Run UNet=0
Run PostProcess=0
UNET Theta=0
UNET Theta Warmup=0
UNET ZTol=0
UNET ZSATol=0
UNET MxIter=0
UNET MaxInSteps=0
UNET DtIC=0
UNET DtMin=0
UNET MaxCRTS=0
UNET WFStab=0
UNET SFStab=0
UNET WFX=0
UNET SFX=0
UNET DSS MLevel=0
UNET DZMax Abort=0
UNET Convert EG Bridges=0
UNET Use Existing IB Tables=0
UNET Froude Limit=0
UNET Froude Power=0
Write IC File=0
Echo Input=False
Echo Output=False
Write Detailed=0

--- HOKERUNTRB.f01 (steady flow) ---

Flow Title=NFF Regression Equation
Program Version=5.03
Number of Profiles= 1
Profile Names=P100yr
River Rch & RM=HOKERUNTRB,Main            ,2913.6
590.0465
River Rch & RM=HOKERUNTRB,Main            ,355.4
612.8122
River Rch & RM=HOKERUNTRB,Main            ,252.4
613.9844
Boundary for River Rch & Prof#=HOKERUNTRB,Main            , 1
Up Type= 0
Dn Type= 3
Dn Slope=0.0108
DSS Import GetInterval= 0
DSS Import GetPeak= 0
DSS Import FillOption= 0

--- HOKERUNTRB.g01 (geometry) ---

Geom Title=USGS 10m DEM
Program Version=4.10

River Reach=HOKERUNTRB      ,Main
Reach XY= 30
     2409302.187      369072.655     2409296.111      369111.717
     2409320.417      369238.453     2409406.354      369371.266
     2409513.993      369636.023     2409602.535      369786.196
     2409659.155      369831.827      2409718.42      369913.041
     2409712.344      369932.572     2409781.788      370035.437
     2409764.861      370062.347     2409645.377      370125.498
     2409607.399       370164.56     2409638.867      370271.982
     2409728.927      370373.979     2409760.394      370445.593
     2409843.067      370675.143     2409828.853       370731.35
     2409836.349      370786.305     2409860.221      370817.772
     2409857.776      370980.641      2409839.72      371024.738
     2409848.748      371045.224     2409819.697      371198.075
     2409794.567       371251.46     2409801.181      371279.654
     2409758.907      371315.158     2409728.004      371368.543
     2409683.299      371380.696     2409527.155      371511.384

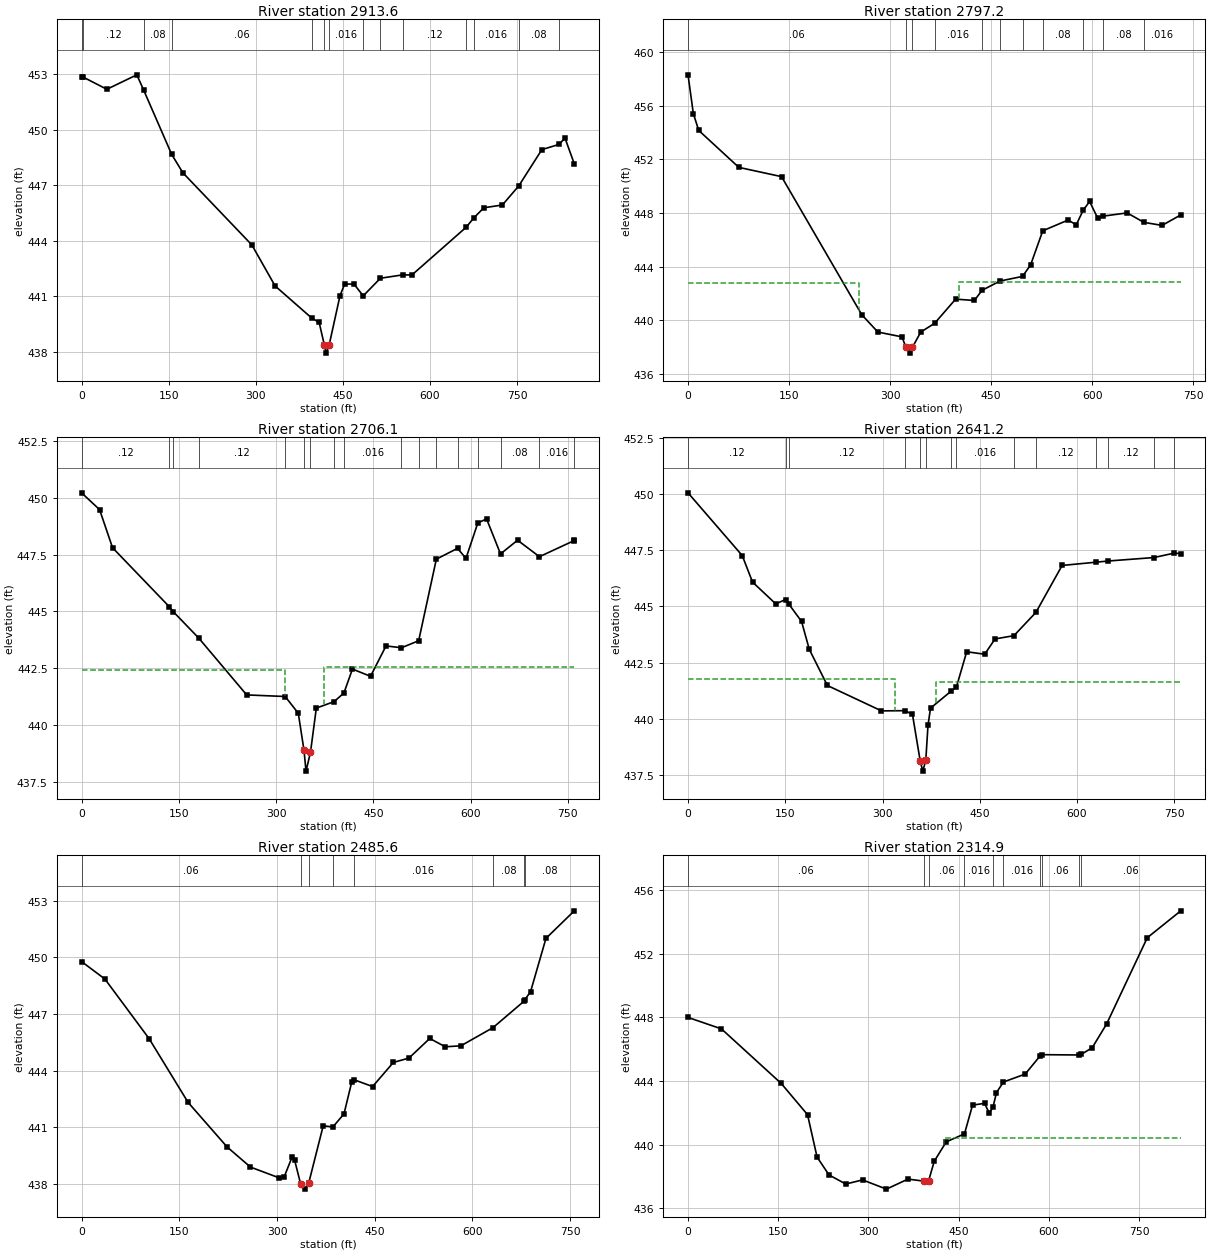
Type RM Length L Ch R = 1 ,2913.6  ,118.8,116.4,114.3
XS GIS Cut Line= 3
     2408882.549      369031.131     2409171.178      369102.745
     2409720.223      369052.832
#Sta/Elev= 30
       0  452.85     2.5  452.85    43.6  452.19    95.2  452.97  107.17452.1318
  155.18448.6766   174.5  447.68   293.4  443.78   333.3  441.57  396.07439.8438
   409.2   439.6  418.11 438.388   421.2  437.94   426.3438.3586   445.2  441.05
   453.2  441.67   469.2  441.67  485.11441.0316   514.7 441.984  553.22442.1666
     569  442.16  662.67444.7452  675.49445.2407   692.9  445.79   724.8  445.94
  752.89446.9652   792.8  448.93  821.96449.2083   832.7  449.55   848.7  448.16
#Mann= 14 ,-1 , 0
       0     .08       0     2.5     .12       0  107.17     .08       0
  155.18     .06       0  396.07    .016       0  418.11    .045       0
   426.3    .016       0  485.11     .06       0   514.7    .016       0
  553.22     .12       0  662.67     .08       0  675.49    .016       0
  752.89     .08       0  821.96     .12       0
Bank Sta=418.11,426.3
XS Rating Curve= 0 ,0
Exp/Cntr=0.3,0.1

Type RM Length L Ch R = 1 ,2797.2  ,94.3,91.1,87.3
XS GIS Cut Line= 3
     2408986.357      369227.902     2409220.385      369225.124
     2409707.885      369126.513
#Sta/Elev= 30
       0  458.29     7.9   455.4    15.9  454.15    75.4   451.4   138.8  450.71
   257.9  440.43   281.8  439.14   317.6  438.78     323438.0565   329.5  437.57
     333437.9987   345.5  439.14  366.08439.7923   397.2  441.59     425  441.49
   436.5442.2487  463.07442.9373  496.52443.2819   508.6  444.15  526.54446.6785
   564.3  447.48   576.2  447.12  586.56448.2117   596.1  448.86   608.1  447.62
  616.58447.7716   651.8  448.01  676.68447.3053   703.6  447.08   731.4  447.86
#Mann= 11 ,-1 , 0
       0     .06       0     323    .045       0     333     .06       0
  366.08    .016       0   436.5     .08       0  463.07    .016       0
  496.52     .12       0  526.54     .08       0  586.56     .12       0
  616.58     .08       0  676.68    .016       0
#XS Ineff= 2 , 0
          254.28  442.77  402.06          442.85
Permanent Ineff=
       F       F
Bank Sta=323,333
XS Rating Curve= 0 ,0
Exp/Cntr=0.3,0.1

Type RM Length L Ch R = 1 ,2706.1  ,65,64.9,65
XS GIS Cut Line= 2
     2409023.163      369409.846     2409735.663      369145.263
#Sta/Elev= 30
       0  450.23    27.8  449.49    47.8  447.81  135.63445.1993  141.62444.9848
   180.6  443.83   254.7  441.32  314.05  441.25   334.3  440.51   343.1438.8745
   346.2  437.96   353.1438.7937   362.1  440.74  389.45441.0227  404.68441.4051
   417.8  442.46   445.7  442.14   469.6  443.48  493.44443.3997  519.94443.7086
  547.22447.3058  579.89447.7822   592.9  447.34  611.18 448.903   624.7  449.08
  646.17447.5367   672.5  448.14  706.21447.4143  759.74 448.124     760  448.13
#Mann= 17 ,-1 , 0
       0     .12       0  135.63     .08       0  141.62     .06       0
   180.6     .12       0  314.05     .06       0   343.1    .045       0
   353.1     .06       0  389.45     .08       0  404.68    .016       0
  493.44     .08       0  519.94     .12       0  547.22     .08       0
  579.89     .06       0  611.18     .12       0  646.17     .08       0
  706.21    .016       0  759.74     .12       0
#XS Ineff= 2 , 0
          313.73  442.43  373.99          442.54
Permanent Ineff=
       F       F
Bank Sta=343.1,353.1
XS Rating Curve= 0 ,0
Exp/Cntr=0.3,0.1

Type RM Length L Ch R = 1 ,2641.2  ,156.1,155.6,155.1
XS GIS Cut Line= 2
     2409041.218      369471.652     2409753.718      369207.068
#Sta/Elev= 30
       0  450.05    83.6  447.26    99.5  446.08   135.3  445.11  150.43445.3035
  155.03445.1176   175.1  444.33     187  443.09   214.9  441.48   298.4  440.35
  335.06440.3592   346.2  440.19   358.1  438.12   362.1  437.67  366.76438.1627
   370.1   439.7     374  440.47  405.38441.2187  413.92441.4075   429.8  442.98
   457.6  442.87   473.5  443.55  502.68 443.696  536.51444.7286     577  446.82
  629.69446.9651  647.94447.0168   718.3447.1705   749.6 447.365     760  447.35
#Mann= 14 ,-1 , 0
       0     .12       0  150.43     .08       0  155.03     .12       0
  335.06     .06       0   358.1    .045       0  366.76     .06       0
  405.38     .08       0  413.92    .016       0  502.68     .08       0
  536.51     .12       0  629.69     .06       0  647.94     .12       0
   718.3     .08       0   749.6    .016       0
#XS Ineff= 2 , 0
          318.68  441.76  383.08          441.65
Permanent Ineff=
       F       F
Bank Sta=358.1,366.76
XS Rating Curve= 0 ,0
Exp/Cntr=0.3,0.1

Type RM Length L Ch R = 1 ,2485.6  ,171.5,170.7,169.8
XS GIS Cut Line= 3
     2409126.635      369615.402     2409693.302      369378.596
     2409834.968      369367.485
#Sta/Elev= 30
       0  449.78    35.9  448.85   103.7  445.69   163.5  442.31   223.3  439.95
   259.2  438.88   303.1  438.31   311.1  438.37     323   439.4     327  439.25
  336.27437.9828     343  437.71   348.5438.0125   370.9  441.07  385.73441.0073
   402.8   441.7   414.8  443.41   417.5443.5208   446.7  443.15   478.6  444.43
   502.5  444.66   534.4   445.7   558.3  445.26   582.2  445.31  631.61446.2778
  679.05 447.675  679.86447.7236   689.2  448.19   712.8  451.01   756.3  452.47
#Mann= 8 ,-1 , 0
       0     .06       0  336.27    .045       0   348.5     .06       0
  385.73     .08       0   417.5    .016       0  631.61     .08       0
  679.05     .12       0  679.86     .08       0
Bank Sta=336.27,348.5
XS Rating Curve= 0 ,0
Exp/Cntr=0.3,0.1

Type RM Length L Ch R = 1 ,2314.9  ,138.9,137.5,136.1
XS GIS Cut Line= 3
     2409156.019       369802.78     2409528.111      369632.025
     2409898.367      369456.096
#Sta/Elev= 30
       0     448    55.6  447.28     155  443.85   198.7  441.89   214.6  439.22
   234.5   438.1   262.3  437.53   290.2  437.79   329.9  437.21   365.7  437.84
  391.59437.7146     400437.7292   409.4  438.96   429.3  440.18  459.63440.6833
   473.1  442.49     493   442.6   500.9  441.99   507.1442.3665   512.9  443.28
  524.47443.9426   560.6  444.44  584.98 445.562  589.32445.6602  649.64445.6408
  654.16445.6845   672.1   446.1     696  447.59   763.6  453.01   819.3   454.7
#Mann= 10 ,-1 , 0
       0     .06       0  391.59    .045       0     400     .06       0
  459.63    .016       0   507.1     .06       0  524.47    .016       0
  584.98     .08       0  589.32     .06       0  649.64     .12       0
  654.16     .06       0
#XS Ineff= 2 , 0
                          426.21          440.43
Permanent Ineff=
       F       F
Bank Sta=391.59,400
XS Rating Curve= 0 ,0
Exp/Cntr=0.3,0.1

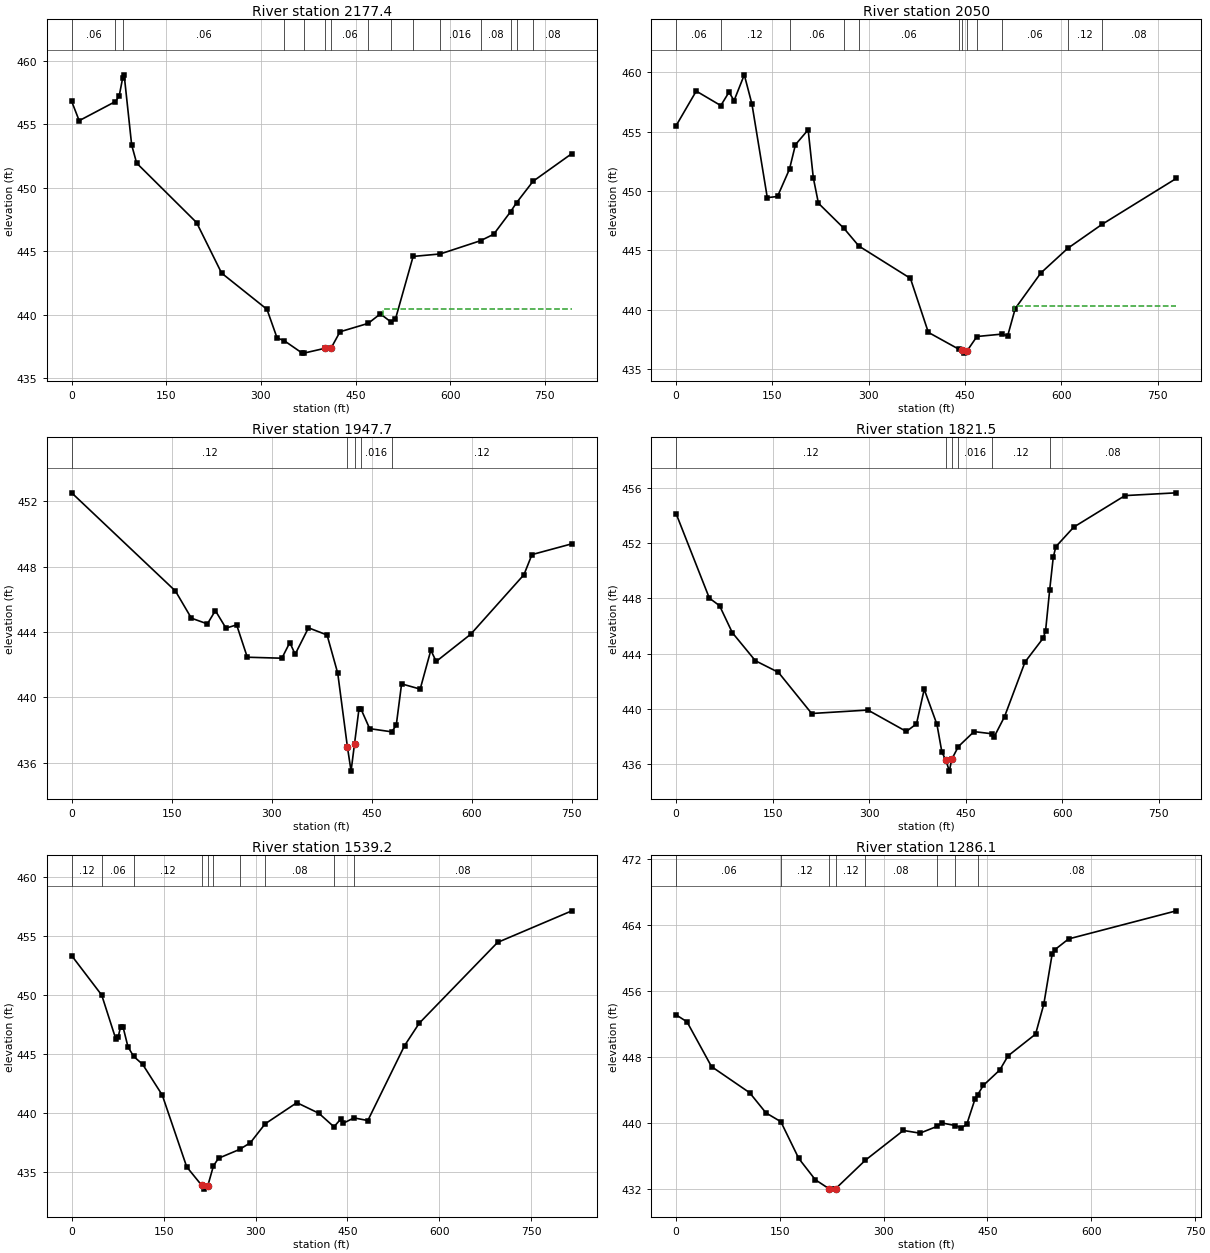
Type RM Length L Ch R = 1 ,2177.4  ,127.3,127.4,127.4
XS GIS Cut Line= 3
     2409304.138      370036.416      2409430.44      369839.801
     2409922.627      369574.176
#Sta/Elev= 30
       0  456.79    11.9  455.27   69.29 456.775    75.3  457.21   80.77458.6127
    83.2  458.88    95.1  453.36     103  451.93     198  447.25   237.7  443.27
   309.6  440.42   325.6  438.17  337.37437.9352   365.5  436.97  368.85436.9784
   401.5  437.35  411.19437.3606   425.4  438.65  470.05439.3125   489.4  440.06
  506.22439.4225   513.3  439.65  541.33444.5829  584.47444.7799  648.31445.8233
   669.1  446.33  695.74448.0984  705.33448.8149  731.49450.5003     793  452.68
#Mann= 15 ,-1 , 0
       0     .06       0   69.29     .12       0   80.77     .06       0
  337.37     .12       0  368.85     .06       0   401.5    .045       0
  411.19     .06       0  470.05    .016       0  506.22     .06       0
  541.33     .08       0  584.47    .016       0  648.31     .08       0
  695.74    .016       0  705.33     .06       0  731.49     .08       0
#XS Ineff= 2 , 0
                          492.88          440.41
Permanent Ineff=
       F       F
Bank Sta=401.5,411.19
XS Rating Curve= 0 ,0
Exp/Cntr=0.3,0.1

Type RM Length L Ch R = 1 ,2050    ,102.1,102.3,99.3
XS GIS Cut Line= 3
      2409312.28      370098.275     2409357.853       370015.81
     2409961.152      369692.459
#Sta/Elev= 30
       0  455.49    31.4  458.41   69.62457.1894    82.4  458.32    90.3  457.61
   106.2  459.78   118.1  457.32     142  449.43   157.9  449.53  176.58451.8362
   185.8  453.89   205.6  455.15   213.6  451.12   221.6  448.96  261.43446.8376
  284.57445.3545   364.8  442.63   392.7  438.08  439.95436.6673   444.4  436.56
   448.4  436.33   452.4  436.47  468.34437.7302  507.95437.9364   516.1  437.76
     528  440.09   567.8  443.08  609.82445.1644  663.21447.1835   778.7  451.05
#Mann= 12 ,-1 , 0
       0     .06       0   69.62     .12       0  176.58     .06       0
  261.43     .12       0  284.57     .06       0  439.95     .12       0
   444.4    .045       0   452.4     .12       0  468.34    .016       0
  507.95     .06       0  609.82     .12       0  663.21     .08       0
#XS Ineff= 2 , 0
                          526.73          440.28
Permanent Ineff=
       F       F
Bank Sta=444.4,452.4
XS Rating Curve= 0 ,0
Exp/Cntr=0.3,0.1

Type RM Length L Ch R = 1 ,1947.7  ,133.9,126.2,151.5
XS GIS Cut Line= 2
     2409343.053      370131.391     2410004.945      369777.659
#Sta/Elev= 30
       0  452.52   155.7  446.51   179.6  444.85   203.6   444.5   215.6  445.31
   231.5  444.24   247.5  444.44   263.5  442.46   315.4   442.4   327.3  443.36
   335.3  442.64   355.3  444.26   383.2  443.82   399.2  441.48   413.7436.9763
   419.2  435.49  424.41437.1777   431.1   439.3  433.97   439.3   447.1  438.09
  480.21437.8946     487   438.3     495  440.83   522.9  440.51   538.9  442.89
   546.9   442.2   598.8  443.87   678.6  447.51   690.6  448.74   750.5   449.4
#Mann= 5 ,-1 , 0
       0     .12       0   413.7    .045       0  424.41     .12       0
  433.97    .016       0  480.21     .12       0
Bank Sta=413.7,424.41
XS Rating Curve= 0 ,0
Exp/Cntr=0.3,0.1

Type RM Length L Ch R = 1 ,1821.5  ,291.7,282.3,262.2
XS GIS Cut Line= 4
     2409409.893      370232.954     2409760.909      370030.021
     2409824.711      370056.497     2410089.902      369910.403
#Sta/Elev= 30
       0  454.14    51.7  448.02    67.6  447.47    87.4  445.52   123.2  443.49
     159  442.65   210.7  439.67   298.1  439.92   357.8  438.37   373.6  438.92
   385.6  441.42   405.4  438.88   413.1  436.87   419.5436.2742   424.6   435.5
   428.5  436.37  438.66437.2765     463  438.36  490.26438.2062   494.4  437.99
   510.4  439.44   542.3   443.4   570.1   445.1   574.1  445.61  580.63448.6372
   586.1  450.96   590.1  451.74     618  453.16   697.6  455.44   777.3  455.64
#Mann= 6 ,-1 , 0
       0     .12       0   419.5    .045       0   428.5     .12       0
  438.66    .016       0  490.26     .12       0  580.63     .08       0
Bank Sta=419.5,428.5
XS Rating Curve= 0 ,0
Exp/Cntr=0.3,0.1

Type RM Length L Ch R = 1 ,1539.2  ,252.4,253.1,253.4
XS GIS Cut Line= 3
     2409435.935      370316.938     2410056.594      370004.438
     2410177.141      369992.131
#Sta/Elev= 30
       0  453.31   49.01 449.974    71.9  446.28    75.9  446.45    79.9   447.3
    83.9  447.26    91.8  445.61  100.91444.8045   115.8  444.12   147.8  441.52
   187.7  435.45   212.1 433.894   215.7  433.57   222.1433.8525   231.3435.5372
   239.6  436.18  273.92 436.927   291.5  437.49  315.61 439.088   367.4  440.88
   403.4  439.98  427.94438.8388   439.3  439.51   443.3  439.15  460.71439.5917
   483.2  439.37   543.1   445.7   567.1   447.6   694.9  454.43   816.1   457.1
#Mann= 10 ,-1 , 0
       0     .12       0   49.01     .06       0  100.91     .12       0
   212.1    .045       0   222.1     .12       0   231.3     .08       0
  273.92     .06       0  315.61     .08       0  427.94    .016       0
  460.71     .08       0
Bank Sta=212.1,222.1
XS Rating Curve= 0 ,0
Exp/Cntr=0.3,0.1

Type RM Length L Ch R = 1 ,1286.1  ,289.8,303.5,312.5
XS GIS Cut Line= 4
      2409532.61      370480.412       2409692.3      370456.925
     2410054.528      370282.929     2410214.034      370285.099
#Sta/Elev= 30
       0  453.13    15.8  452.28    51.2  446.85   106.3  443.68   129.9  441.23
  151.36440.1666   177.3   435.7   201.2  433.12   220.6  432.05   225.1  431.98
   230.6 432.036  273.48435.4863   328.5   439.1   352.4  438.77  377.02439.5924
   384.2  440.01  403.47439.6905   412.1  439.41     420  439.83     432  442.92
  435.95443.4475   443.9  444.56   467.8  446.44   479.7  448.15   519.5  450.79
   531.4  454.43   543.4  460.48   547.3  461.03   567.2  462.34   722.8  465.75
#Mann= 8 ,-1 , 0
       0     .06       0  151.36     .12       0   220.6    .045       0
   230.6     .12       0  273.48     .08       0  377.02    .016       0
  403.47     .12       0  435.95     .08       0
Bank Sta=220.6,230.6
XS Rating Curve= 0 ,0
Exp/Cntr=0.3,0.1

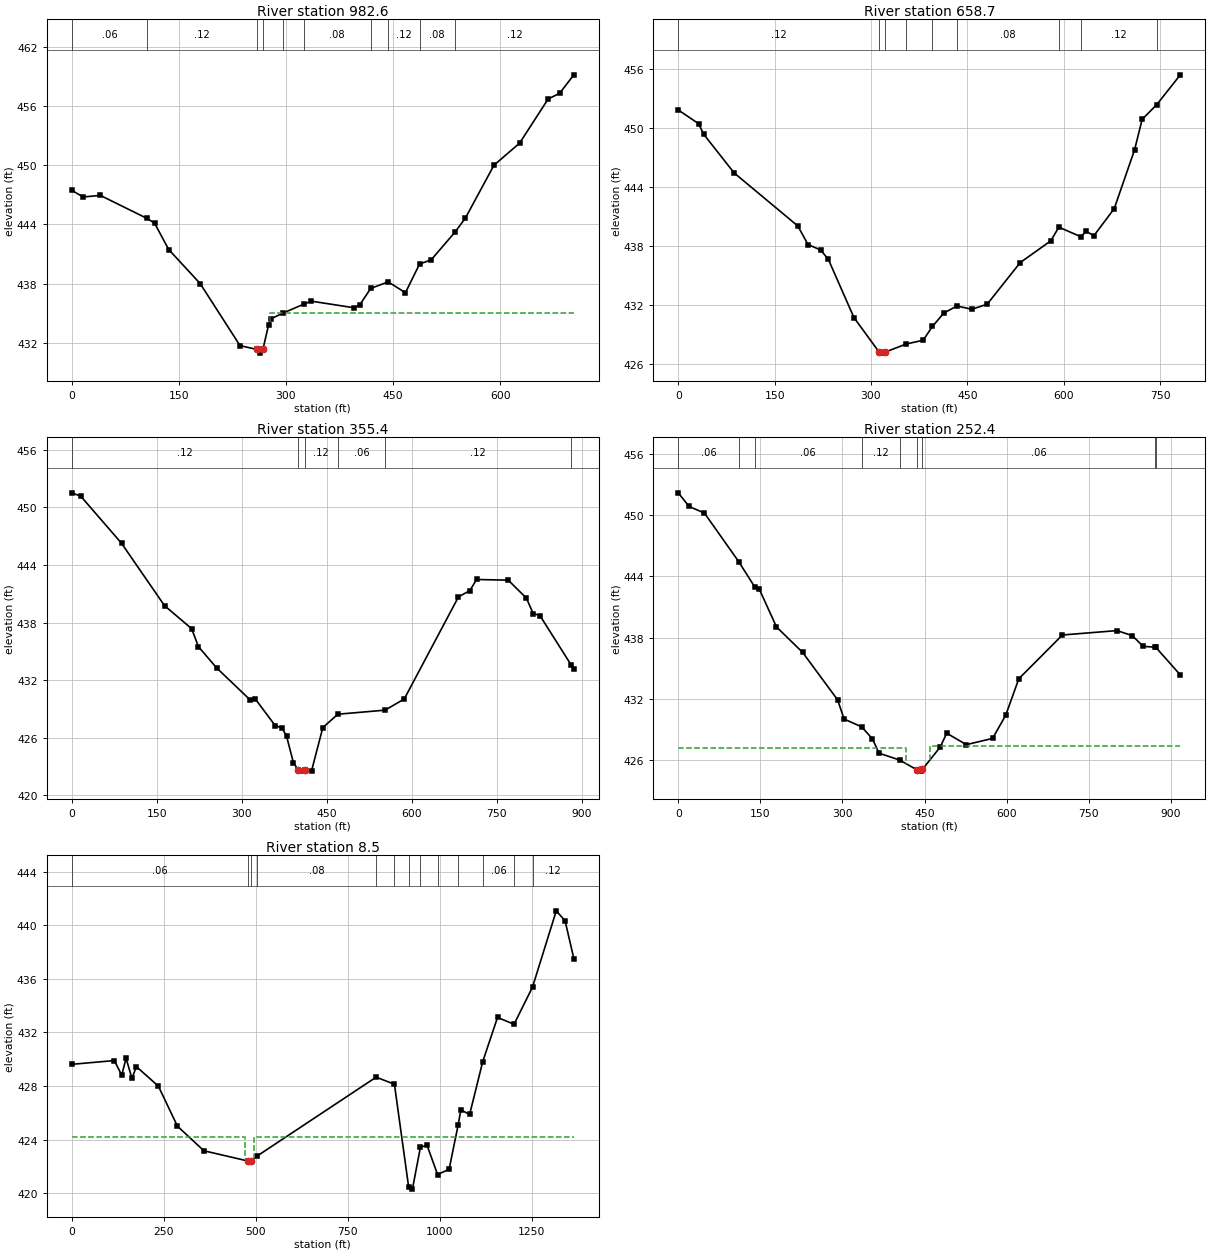
Type RM Length L Ch R = 1 ,982.6   ,312.9,323.9,333.8
XS GIS Cut Line= 3
     2409563.404      370732.629     2410016.899      370690.662
       2410248.3        370601.9
#Sta/Elev= 30
       0  447.45      16  446.78      40  446.94  105.47444.6019   115.9  444.13
   135.8  441.45   179.8     438   235.7   431.7   259.7  431.31   263.7  430.94
   267.7  431.31   275.7   433.8   279.6  434.44  295.19434.9795  324.78435.9013
   335.6  436.21   395.5  435.54   403.5  435.84  418.69437.4994  443.17  438.17
   467.4  437.07  487.21439.9815   503.4   440.4  536.83443.2159   551.4  444.64
   591.4     450   627.3  452.24   667.3  456.72   683.3  457.29   703.3  459.17
#Mann= 10 ,-1 , 0
       0     .06       0  105.47     .12       0   259.7    .045       0
   267.7     .12       0  295.19     .06       0  324.78     .08       0
  418.69    .016       0  443.17     .12       0  487.21     .08       0
  536.83     .12       0
#XS Ineff= 2 , 0
                           277.4          435.02
Permanent Ineff=
       F       F
Bank Sta=259.7,267.7
XS Rating Curve= 0 ,0
Exp/Cntr=0.3,0.1

Type RM Length L Ch R = 1 ,658.7   ,287.3,303.3,310.9
XS GIS Cut Line= 4
     2409531.525      370958.927     2409770.898      370991.822
      2409984.98      371068.891     2410271.976      370945.491
#Sta/Elev= 30
       0  451.81    31.7  450.41    39.6  449.34    87.1  445.41   186.2  440.03
     202  438.15   221.8  437.59   233.7  436.64   273.6  430.73   312.4427.2655
   317.5  427.13   322.4427.2411  354.69428.0522   381.3  428.44  395.74429.8362
   413.3  431.19  433.82431.9107   457.2  431.58     481   432.1   532.4  436.32
   579.9  438.52  592.53439.9104  626.64438.9477   635.2  439.48   647.1  439.05
   678.7  441.79   710.4  447.76   722.2  450.85  744.94452.3491   781.6  455.37
#Mann= 9 ,-1 , 0
       0     .12       0   312.4    .045       0   322.4     .12       0
  354.69     .06       0  395.74     .12       0  433.82     .08       0
  592.53    .016       0  626.64     .12       0  744.94     .08       0
Bank Sta=312.4,322.4
XS Rating Curve= 0 ,0
Exp/Cntr=0.3,0.1

Type RM Length L Ch R = 1 ,355.4   ,101.8,103,103
XS GIS Cut Line= 2
     2409542.202      370976.393     2410091.681      371671.706
#Sta/Elev= 30
       0  451.53      16  451.17    87.8  446.27   163.7  439.76   211.6  437.36
   223.6  435.48   255.5  433.28   315.4   429.9   323.4  430.07   359.3  427.23
   371.2  427.01   379.2  426.12   391.2  423.39   399.2  422.66   403.2   422.5
   411.2  422.63   423.2  422.52   443.1  427.04  469.55428.4356  552.89428.8597
   586.8  430.02   682.6  440.68   702.6  441.33   714.6  442.49   770.4  442.42
   802.4  440.55   814.4  438.94   826.3  438.73  881.49 433.571   886.2  433.16
#Mann= 6 ,-1 , 0
       0     .12       0   399.2    .045       0   411.2     .12       0
  469.55     .06       0  552.89     .12       0  881.49     .06       0
Bank Sta=399.2,411.2
XS Rating Curve= 0 ,0
Exp/Cntr=0.3,0.1

Type RM Length L Ch R = 1 ,252.4   ,244.1,243.9,242.7
XS GIS Cut Line= 2
     2409459.476      371018.407     2410019.372       371744.97
#Sta/Elev= 30
       0  452.21    19.9  450.87    47.9  450.22  110.43445.4629   139.6  442.99
   147.6  442.82   179.5  439.05   227.3  436.55   291.1   431.9   303.1  430.01
  335.21429.2437   354.9  428.06   366.9  426.66  404.31425.9934   436.1 425.029
   442.7   424.9   446.1  425.07   478.6  427.26   490.5  428.62   526.4   427.5
   574.3  428.11   598.2  430.37   622.2  433.96   701.9  438.26   801.6  438.69
   829.5   438.2   849.5  437.14  871.91437.0635  872.59437.0482   917.3  434.34
#Mann= 9 ,-1 , 0
       0     .06       0  110.43     .12       0   139.6     .06       0
  335.21     .12       0  404.31     .06       0   436.1    .045       0
   446.1     .06       0  871.91     .12       0  872.59     .06       0
#XS Ineff= 2 , 0
          415.89  427.21  459.24          427.39
Permanent Ineff=
       F       F
Bank Sta=436.1,446.1
XS Rating Curve= 0 ,0
Exp/Cntr=0.3,0.1

Type RM Length L Ch R = 1 ,8.5     ,7.4,8.5,9.6
XS GIS Cut Line= 3
     2409204.268      371148.616     2409793.902      371788.234
     2409610.518      372247.574
#Sta/Elev= 30
       0  429.62   115.7   429.9   135.7  428.81   147.6  430.07   163.6  428.57
   175.6  429.45   235.4  427.99   287.3     425   359.2  423.17  478.51422.4095
  487.51422.4021  504.47422.7917  827.18428.6612  876.87428.1356  915.63420.4493
   925.8  420.31  947.63423.4496   965.7  423.57  994.14421.3987  1025.5  421.79
 1049.91425.0735  1057.4  426.22  1081.3  425.88 1116.74 429.811  1157.1  433.12
 1201.93432.6049 1252.21435.3836  1316.7  441.07  1340.6  440.33  1364.5  437.51
#Mann= 13 ,-1 , 0
       0     .06       0  478.51    .045       0  487.51     .06       0
  504.47     .08       0  827.18    .016       0  876.87     .08       0
  915.63     .12       0  947.63    .016       0  994.14     .06       0
 1049.91     .12       0 1116.74     .06       0 1201.93    .016       0
 1252.21     .12       0
#XS Ineff= 2 , 0
          469.46  424.19  494.15           424.2
Permanent Ineff=
       F       F
Bank Sta=478.51,487.51
XS Rating Curve= 0 ,0
Exp/Cntr=0.3,0.1

Chan Stop Cuts=-1
Use User Specified Reach Order=0
Composite Channel Slope=5